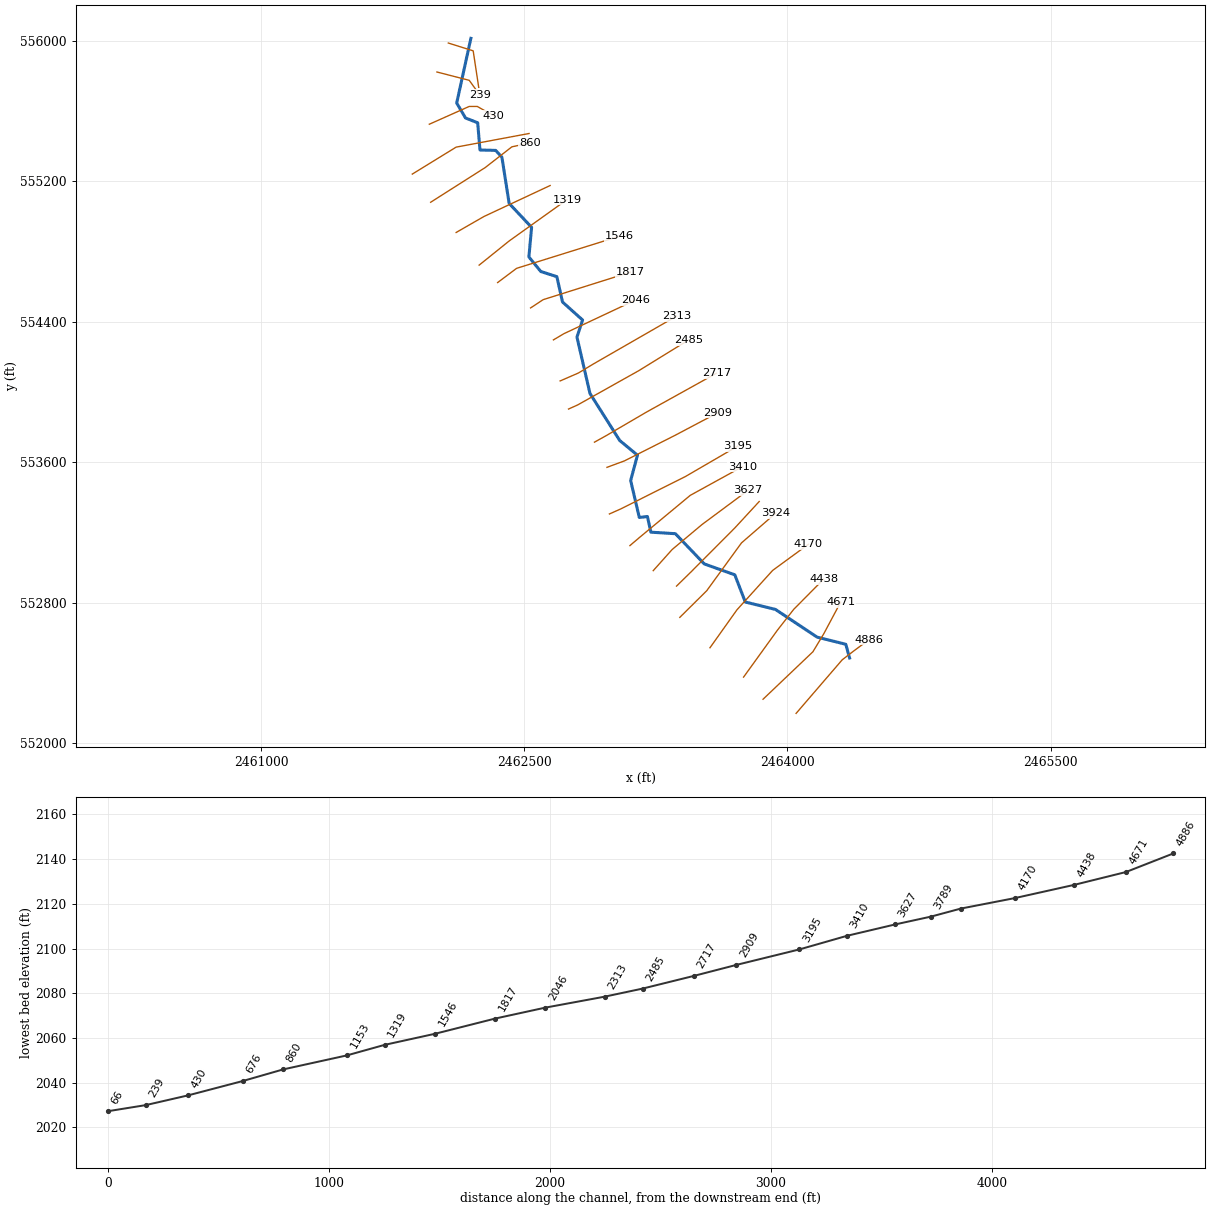
--- WOLFRN.prj (project) ---

Proj Title=WOLFRN
Current Plan=p01
Default Exp/Contr=0,0
English Units
Geom File=g01
Flow File=f01
Plan File=p01
BEGIN DESCRIPTION:
Stream Name:Wolf Run
Flood Zone: Zone A
Pendleton County, WV
WVDHSEM Flood Warning & Analysis Mapping
HEC-RAS Version: 5.0.7
Hydrology Method:
Regression was used
Model Notes:
Confluence with Kettle Creek
END DESCRIPTION:
DSS Export Rating Curves= 0
DSS Export Rating Curve Sorted= 0
DSS Export Volume Flow Curves= 0
DXF Filename=H:\CTP\WV\f03_Pendleton_RiskMAP\f05_Engineering\f02_Hydraulics\02_Final\Approximate\WOLFRN\WOLFRN.
DXF OffsetX= 0
DXF OffsetY= 0
DXF ScaleX= 0
DXF ScaleY= 0

--- WOLFRN.p01 (plan) ---

Plan Title=Floodplain
Program Version=5.07
Short Identifier=Floodplain
Geom File=g01
Flow File=f01
Subcritical Flow
K Sum by GR= 0
Std Step Tol= 0.01
Critical Tol= 0.01
Num of Std Step Trials= 20
Max Error Tol= 0.3
Flow Tol Ratio= 0.001
Split Flow NTrial= 30
Split Flow Tol= 0.02
Split Flow Ratio= 0.02
Log Output Level= 0
Friction Slope Method= 1
Unsteady Friction Slope Method= 2
Unsteady Bridges Friction Slope Method= 1
Parabolic Critical Depth
Global Vel Dist= 0 , 0 , 0
Global Log Level= 0
CheckData=True
Encroach Param=-1 ,0,0, 0
Mapping Interval=1HOUR
Computation Time Step Use Courant=        0
Computation Time Step Use Time Series=    0
Computation Time Step Count To Double=0
Computation Time Step Max Doubling=0
Computation Time Step Max Halving=0
Computation Time Step Residence Courant=0
Run HTab= 0
Run UNet= 0
Run Sediment= 0
Run PostProcess= 0
Run WQNet= 0
Run RASMapper= 0
UNET Theta= 0
UNET Theta Warmup= 0
UNET ZTol= 0
UNET ZSATol= 0
UNET MxIter= 0
UNET Max Iter WO Improvement= 0
UNET MaxInSteps= 0
UNET DtIC= 0
UNET DtMin= 0
UNET MaxCRTS= 0
UNET WFStab= 0
UNET SFStab= 0
UNET WFX= 1
UNET SFX= 1
UNET 1D Methodology=Finite Difference
UNET DSS MLevel= 1
UNET Pardiso=0
UNET DZMax Abort= 0
UNET Use Existing IB Tables= 0
UNET Froude Reduction=False
UNET Froude Limit= 0
UNET Froude Power= 0
UNET D1 Cores= 0
UNET D2 Coriolis=0
UNET D2 Cores= 0
UNET D2 Theta= 1
UNET D2 Theta Warmup= 1
UNET D2 Z Tol= 0.01
UNET D2 Volume Tol= 0.01
UNET D2 Max Iterations= 20
UNET D2 Equation= 0
UNET D2 RampUpFraction=0.1
UNET D2 TimeSlices= 1
UNET D2 BCVolumeCheck=0
UNET D1D2 MaxIter= 0
UNET D1D2 ZTol=0.01
UNET D1D2 QTol=0.1
UNET D1D2 MinQTol=1
Write IC File= 0
Write IC File at Fixed DateTime=0
Write IC File at Sim End=0
Echo Input=False
Echo Parameters=False
Echo Output=False
Write Detailed= 0
HDF Write Warmup=0
HDF Write Time Slices=0
HDF Flush=0
HDF Face Node Velocities=0
HDF Compression= 1
HDF Chunk Size= 1
HDF Spatial Parts= 1
HDF Use Max Rows=0
HDF Fixed Rows= 1
Calibration Method= 0
Calibration Iterations= 20
Calibration Max Change=0.05
Calibration Tolerance=0.2
Calibration Maximum=1.5
Calibration Minimum=0.5
Calibration Optimization Method= 1
WQ AD Non Conservative
WQ ULTIMATE=-1
WQ Max Comp Step=1HOUR
WQ Output Interval=15MIN
WQ Output Selected Increments= 0
WQ Output face flow=0
WQ Output face velocity=0
WQ Output face area=0
WQ Output face dispersion=0
WQ Output cell volume=0
WQ Output cell surface area=0
WQ Output cell continuity=0
WQ Output cumulative cell continuity=0
WQ Output face conc=0
WQ Output face dconc_dx=0
WQ Output face courant=0
WQ Output face peclet=0
WQ Output face adv mass=0
WQ Output face disp mass=0
WQ Output cell mass=0
WQ Output cell source sink temp=0
WQ Output nsm pathways=0
WQ Output nsm derived pathways=0
WQ Output MaxMinRange=-1
WQ Daily Max Min Mean=-1
WQ Daily Range=0
WQ Daily Time=0
WQ Create Restart=0
WQ Fixed Restart=0
WQ System Summary=0
WQ Write To DSS=0
WQ Use Fixed Temperature=0
Sorting and Armoring Iterations= 10
XS Update Threshold= 0.02
Bed Roughness Predictor= 0
Hydraulics Update Threshold= 0.02
Energy Slope Method= 1
Volume Change Method= 1
Sediment Retention Method= 0
XS Weighting Method= 0
Number of US Weighted Cross Sections= 1
Number of DS Weighted Cross Sections= 1
Upstream XS Weight=0
Main XS Weight=1
Downstream XS Weight=0
Number of DS XS's Weighted with US Boundary= 1
Upstream Boundary Weight= 1
Weight of XSs Associated with US Boundary= 0
Number of US XS's Weighted with DS Boundary= 1
Downstream Boundary Weight= 0.5
Weight of XSs Associated with DS Boundary= 0.5
Percentile Method= 0
Sediment Output Level= 3
Mass or Volume Output= 0
Output Increment Type= 1
Profile and TS Output Increment= 1
XS Output Flag= 0
XS Output Increment= 10
Write Gradation File= 0
Read Gradation Hotstart= 0
Write HDF5 File= 1
Write Binary Output= 1
Write DSS Sediment File= 0
SV Curve= 0
Specific Gage Flag= 0

--- WOLFRN.f01 (steady flow) ---

Flow Title=Flows
Program Version=4.00
Number of Profiles=6
Profile Names=P100yr,P10yr,P25yr,P50yr,P500yr,P101yr
River Rch & RM=WOLFRN,Main      ,4886
     492     230     325     406     719     598
Boundary for River Rch & Prof#=WOLFRN,Main      ,1
Up Type=0
Dn Type=3
Dn Slope=0.024649
Boundary for River Rch & Prof#=WOLFRN,Main      ,2
Up Type=0
Dn Type=3
Dn Slope=0.024649
Boundary for River Rch & Prof#=WOLFRN,Main      ,3
Up Type=0
Dn Type=3
Dn Slope=0.024649
Boundary for River Rch & Prof#=WOLFRN,Main      ,4
Up Type=0
Dn Type=3
Dn Slope=0.024649
Boundary for River Rch & Prof#=WOLFRN,Main      ,5
Up Type=0
Dn Type=3
Dn Slope=0.024649
Boundary for River Rch & Prof#=WOLFRN,Main      ,6
Up Type=0
Dn Type=3
Dn Slope=0.024649

--- WOLFRN.g01 (geometry) ---

Geom Title=Geometry
Program Version=5.07

River Reach=WOLFRN          ,Main
Reach XY= 30
      2464354.53      552484.219     2464332.833      552562.114
     2464169.689      552602.713      2463931.74       552760.85
     2463760.239      552802.876     2463700.354      552958.077
     2463526.548      553019.933     2463361.803      553192.269
     2463222.088      553200.955     2463202.422      553290.217
     2463156.158      553284.784     2463106.934      553495.437
     2463145.752      553639.804     2463044.408      553723.583
     2462874.996      553991.672     2462800.905      554312.683
     2462832.988      554409.892     2462718.521      554512.733
     2462686.324      554657.134     2462594.897      554686.426
     2462526.984      554769.355     2462542.405      554938.257
     2462414.525      555074.384     2462373.123      555338.285
     2462337.785      555376.603     2462248.169      555378.978
     2462235.213      555533.969     2462165.852      555561.366
     2462115.525      555646.488     2462196.406      556015.269

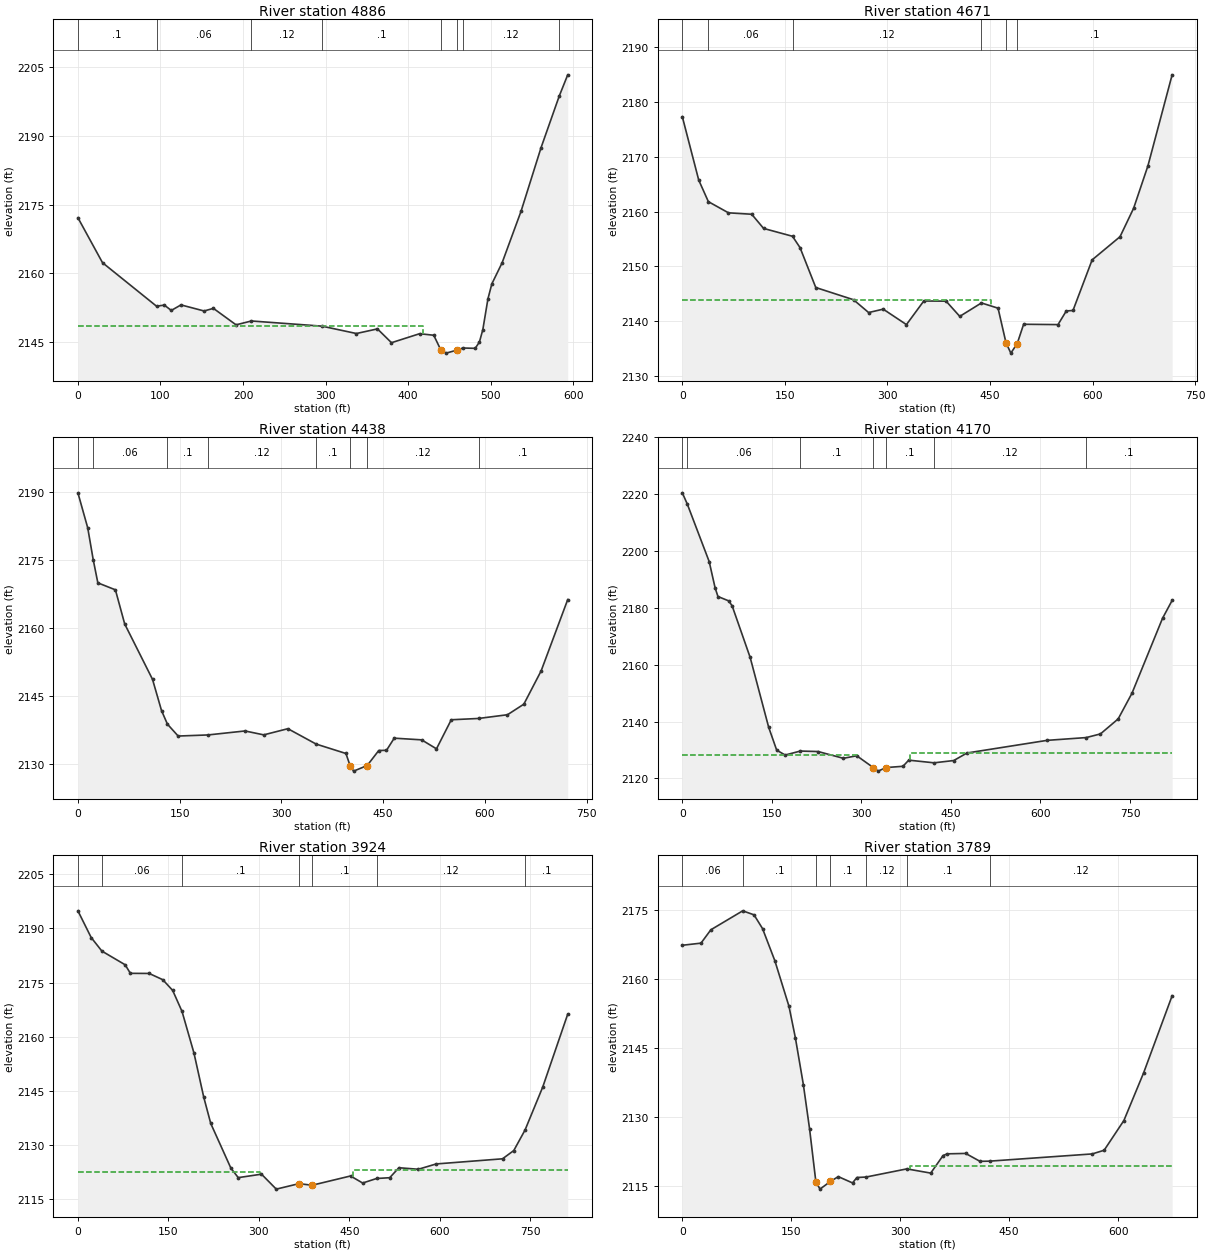
Type RM Length L Ch R = 1 ,4886    ,212.2,215.3,219.7
XS GIS Cut Line= 4
2464049.82372764552168.3375288342464312.77258424552473.844581871
2464384.20955684552528.5622630122464464.76614296552587.839750915
#Sta/Elev= 30
       0 2172.13    29.8 2162.29   95.24 2152.77   104.6 2153.02   113.1 2151.85
   124.8 2153.06   152.8 2151.73   164.1  2152.3   191.5  2148.7  210.112149.542
  295.512148.412   337.2  2146.8   362.7 2147.81   379.7 2144.79   413.8 2146.76
   430.9 2146.42   439.5 2143.18   445.9 2142.51   459.4 2143.19  465.882143.629
   481.1 2143.56   486.2 2144.95   490.3 2147.64   496.5 2154.39   501.2 2157.65
   513.7 2162.29   536.6 2173.55   560.8 2187.45  582.882198.771   593.1 2203.39
#Mann= 8 ,-1 , 0
       0      .1       0   95.24     .06       0  210.11     .12       0
  295.51      .1       0   439.5    .045       0   459.4      .1       0
  465.88     .12       0  582.88      .1       0
#XS Ineff= 2 , 0
          417.62  2148.5
Permanent Ineff=
       F       F
Bank Sta=439.5,459.4
XS Rating Curve= 0 ,0
Exp/Cntr(USF)=0,0
Exp/Cntr=0.3,0.1

Type RM Length L Ch R = 1 ,4671    ,234.5,233,228.6
XS GIS Cut Line= 4
2463861.35171482552248.8941149582464145.57966964552519.442649488
2464207.89702872552622.7982694212464303.65297071552802.150668717
#Sta/Elev= 30
       0 2177.34      24 2165.77   38.092161.831    67.5 2159.79   101.5 2159.53
   118.9 2156.94  161.162155.507   172.2 2153.43   195.2 2146.15   250.4 2143.92
   272.5 2141.58   293.8  2142.2   327.8 2139.38   353.2 2143.69   385.8 2143.66
   405.8 2140.88  437.482143.333   461.8 2142.38   473.42136.068   480.5 2134.17
   489.8 2135.91   499.2 2139.44   549.5 2139.38   561.6 2141.87   571.4 2141.96
   599.4  2151.2   640.2 2155.43   660.1 2160.63     681 2168.37   716.4 2184.99
#Mann= 6 ,-1 , 0
       0      .1       0   38.09     .06       0  161.16     .12       0
  437.48      .1       0   473.4    .045       0   489.8      .1       0
#XS Ineff= 2 , 0
          451.61 2143.95
Permanent Ineff=
       F       F
Bank Sta=473.4,489.8
XS Rating Curve= 0 ,0
Exp/Cntr(USF)=0,0
Exp/Cntr=0.3,0.1

Type RM Length L Ch R = 1 ,4438    ,268.5,267.8,266.3
XS GIS Cut Line= 4
2463750.39641695  552375.04876872463943.42823653552642.557432056
2464036.14430736552761.1124078612464206.37709313552932.865129221
#Sta/Elev= 30
       0 2189.85    14.5 2182.11   22.532175.133    29.4 2169.99    55.3 2168.45
      69 2160.92     110 2148.71   123.3 2141.81  131.982138.829   147.8  2136.2
  191.65 2136.44   246.4 2137.32     274 2136.46   309.6 2137.82   351.32134.425
   395.2 2132.35   401.4 2129.63   406.5 2128.46   426.5 2129.69   443.6 2133.01
     455 2133.05   466.4 2135.73   506.8 2135.36   528.7 2133.38   550.5 2139.79
  590.82 2140.08   633.4  2140.9   657.5 2143.23     683 2150.57   722.2  2166.3
#Mann= 8 ,-1 , 0
       0      .1       0   22.53     .06       0  131.98      .1       0
  191.65     .12       0   351.3      .1       0   401.4    .045       0
   426.5     .12       0  590.82      .1       0
Bank Sta=401.4,426.5
XS Rating Curve= 0 ,0
Exp/Cntr(USF)=0,0
Exp/Cntr=0.3,0.1

Type RM Length L Ch R = 1 ,4170    ,242.6,245.4,245.6
XS GIS Cut Line= 4
2463558.88453296552542.2416832972463712.39802727552758.072536687
2463916.06939596  552983.02300362464119.74076465 553131.97669115
#Sta/Elev= 30
       0 2220.47    8.322216.523      45 2196.29    54.9 2187.07    59.7 2183.99
    77.8 2182.45    83.5 2180.69   113.7 2162.54   144.7 2137.97   158.1 2129.94
   172.3 2128.22  197.762129.626   227.5 2129.45   269.9 2127.07   292.2 2127.97
   319.9 2123.82     328 2122.56   341.5 2123.82   369.7 2124.26   379.3 2126.42
  421.732125.484   454.8 2126.29   476.9 2128.94   611.3 2133.39  676.592134.362
   700.5 2135.65   730.2 2140.93   753.3 2149.95   804.5 2176.32   820.6 2182.62
#Mann= 7 ,-1 , 0
       0      .1       0    8.32     .06       0  197.76      .1       0
   319.9    .045       0   341.5      .1       0  421.73     .12       0
  676.59      .1       0
#XS Ineff= 2 , 0
          294.04  2128.4  380.89         2128.89
Permanent Ineff=
       F       F
Bank Sta=319.9,341.5
XS Rating Curve= 0 ,0
Exp/Cntr(USF)=0,0
Exp/Cntr=0.3,0.1

Type RM Length L Ch R = 1 ,3924    ,138.9,135,134
XS GIS Cut Line= 4
 2463387.1318116552715.5143402442463540.64530591552867.507898969
2463738.23693225553139.5763690872463934.30862301553309.809154859
#Sta/Elev= 30
       0 2194.87      22 2187.48   39.752183.727    78.3 2179.94      87 2177.57
   118.1 2177.54   140.7 2175.81   157.1 2172.84  172.592167.025   192.4  2155.5
   208.6 2143.29   220.2 2136.02   253.6 2123.65   265.8 2121.03   304.3 2121.99
   328.8 2117.85   366.3 2119.36   388.3 2118.93   451.9 2121.49     472 2119.54
  495.142120.792   516.8 2121.01   532.1 2123.77   564.3 2123.35   593.9 2124.82
   703.8 2126.24   722.5 2128.53  741.122134.192   770.5 2146.11   811.9 2166.27
#Mann= 7 ,-1 , 0
       0      .1       0   39.75     .06       0  172.59      .1       0
   366.3    .045       0   388.3      .1       0  495.14     .12       0
  741.12      .1       0
#XS Ineff= 2 , 0
          301.49 2122.63  455.33         2123.25
Permanent Ineff=
       F       F
Bank Sta=366.3,388.3
XS Rating Curve= 0 ,0
Exp/Cntr(USF)=0,0
Exp/Cntr=0.3,0.1

Type RM Length L Ch R = 1 ,3789    ,163.6,162,160.1
XS GIS Cut Line= 4
2463368.35644247552893.7221824442463449.13205132552972.702777757
2463700.43394549553224.9021786982463839.54749405553375.683315204
#Sta/Elev= 30
       0 2167.33    25.7 2167.79    39.3  2170.7   83.132174.823    98.7 2173.95
   110.4 2170.96   127.4 2163.95   146.8 2154.05   155.6 2147.21   166.6 2137.02
   175.1 2127.45   183.8 2115.89   189.5 2114.26   203.72115.921   214.7 2116.98
   234.3 2115.61   240.3 2116.79  252.842116.889  308.972118.665   341.9 2117.75
   358.9 2121.56   364.6 2121.94     390 2122.03   409.7 2120.31  423.09 2120.35
   564.2 2121.92   580.6 2122.72   607.8 2129.19     635 2139.58   674.2 2156.34
#Mann= 7 ,-1 , 0
       0     .06       0   83.13      .1       0   183.8    .045       0
   203.7      .1       0  252.84     .12       0  308.97      .1       0
  423.09     .12       0
#XS Ineff= 2 , 0
                          313.52         2119.36
Permanent Ineff=
       F       F
Bank Sta=183.8,203.7
XS Rating Curve= 0 ,0
Exp/Cntr(USF)=0,0
Exp/Cntr=0.3,0.1

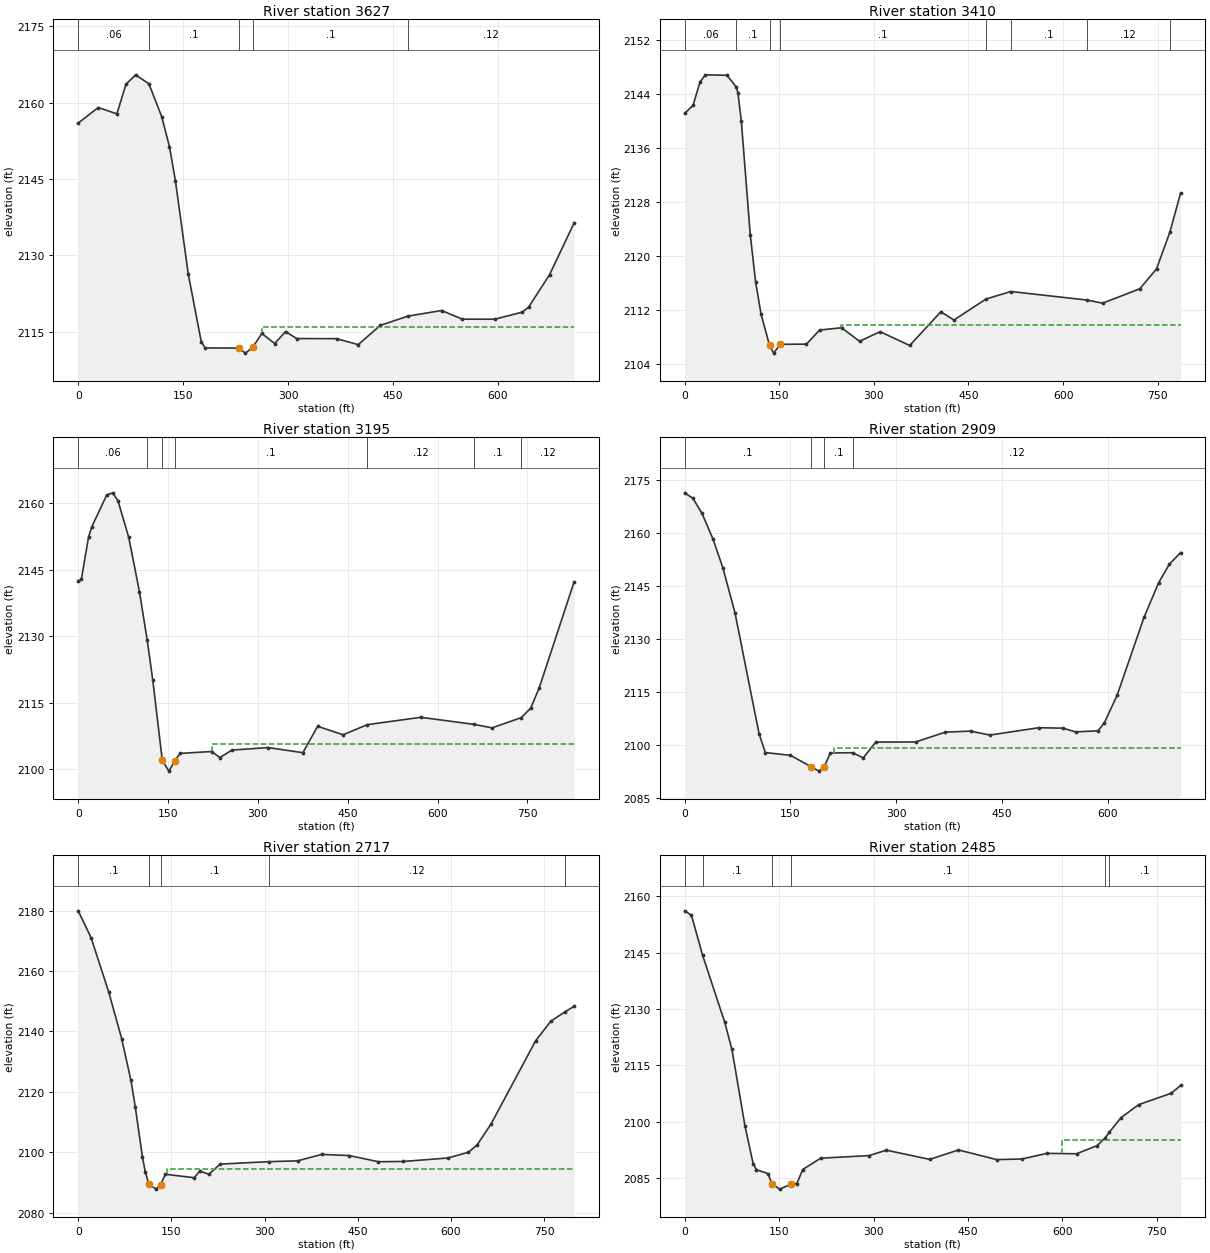
Type RM Length L Ch R = 1 ,3627    ,217.5,217.7,218.9
XS GIS Cut Line= 4
2463235.52544127552981.6778454062463343.22625306553101.943751904
2463513.75253839553244.6473275262463774.92700698553438.508788748
#Sta/Elev= 30
       0    2156    28.6 2159.06    55.3 2157.82    68.3 2163.64    82.2 2165.49
  101.142163.708   119.3 2157.29   130.5 2151.36   139.1 2144.56   157.3 2126.34
     176 2112.97   181.6 2111.78   229.72111.757   239.1 2110.76   249.5  2111.9
   262.6 2114.62     281 2112.64   296.4    2115   312.3 2113.63   369.4  2113.6
   400.4 2112.43   431.9 2116.22  471.772118.045   519.5 2119.14   549.1 2117.44
   595.6 2117.43   634.9 2118.82   644.1 2119.83     674  2126.2   709.1 2136.39
#Mann= 5 ,-1 , 0
       0     .06       0  101.14      .1       0   229.7    .045       0
   249.5      .1       0  471.77     .12       0
#XS Ineff= 2 , 0
                          263.03          2115.8
Permanent Ineff=
       F       F
Bank Sta=229.7,249.5
XS Rating Curve= 0 ,0
Exp/Cntr(USF)=0,0
Exp/Cntr=0.3,0.1

Type RM Length L Ch R = 1 ,3410    ,198.1,215.1,209.6
XS GIS Cut Line= 4
2463102.69444006553124.3814210272463156.54484595553170.154266038
2463446.43953102553410.6860790352463743.51427021 553574.03231025
#Sta/Elev= 30
       0 2141.12    13.2 2142.29    24.5 2145.78      33 2146.81    67.1 2146.74
   81.642145.031    84.4 2144.15    89.8 2139.99     104 2123.15   112.5 2116.22
   121.1 2111.44   134.5 2106.84   140.9 2105.68   151.7 2106.98   193.1 2107.01
   213.9 2109.09   248.9 2109.43   277.3 2107.43   309.9 2108.85   356.8 2106.81
   406.2 2111.79     427 2110.57  477.872113.677  517.222114.787  637.592113.526
   662.7 2113.06   721.7 2115.19   748.2 2118.13  769.342123.556   786.4 2129.34
#Mann= 8 ,-1 , 0
       0     .06       0   81.64      .1       0   134.5    .045       0
   151.7      .1       0  477.87     .12       0  517.22      .1       0
  637.59     .12       0  769.34      .1       0
#XS Ineff= 2 , 0
                          247.15         2109.88
Permanent Ineff=
       F       F
Bank Sta=134.5,151.7
XS Rating Curve= 0 ,0
Exp/Cntr(USF)=0,0
Exp/Cntr=0.3,0.1

Type RM Length L Ch R = 1 ,3195    ,286.1,285.2,284.7
XS GIS Cut Line= 4
2462986.01856062553304.7802807752463050.63904769553333.500497253
2463419.51432807553518.3868908252463717.48657403553691.605696454
#Sta/Elev= 30
       0 2142.35     5.2 2142.81    17.3 2152.39    22.7 2154.68    47.6 2161.85
    57.7 2162.33    66.5 2160.49    84.3 2152.31   102.2 2140.08  115.262129.082
   124.5  2120.1   140.4    2102   151.4  2099.6   161.2 2101.91   170.2  2103.6
     223 2104.02   236.4 2102.65   256.6 2104.34   316.9 2104.91   375.1 2103.76
   399.7  2109.7   442.2  2107.8  482.762110.076   571.9 2111.73  660.332110.151
   690.9 2109.35  739.712111.661   755.4 2113.78   769.9 2118.45     828  2142.3
#Mann= 7 ,-1 , 0
       0     .06       0  115.26      .1       0   140.4    .045       0
   161.2      .1       0  482.76     .12       0  660.33      .1       0
  739.71     .12       0
#XS Ineff= 2 , 0
                          223.33          2105.8
Permanent Ineff=
       F       F
Bank Sta=140.4,161.2
XS Rating Curve= 0 ,0
Exp/Cntr(USF)=0,0
Exp/Cntr=0.3,0.1

Type RM Length L Ch R = 1 ,2909    ,192.4,192.5,194.4
XS GIS Cut Line= 4
2462971.80304385553570.3555556662463071.66281194553607.289990436
2463358.93063793553752.291845459  2463602.424319553880.878396141
#Sta/Elev= 30
       0 2171.28    11.7 2169.72    24.5  2165.5    40.1 2158.26    54.3 2150.02
    71.4 2137.36   105.5 2103.28   114.4 2097.91     150 2097.14   179.62093.876
   190.6 2092.67   197.8 2093.85   206.7  2097.8  238.572097.873   253.3 2096.39
   271.2 2100.88   327.5  2100.9   369.8 2103.68   405.6 2103.97     433 2102.86
   502.4 2104.93   536.6 2104.81   554.7 2103.74   586.4 2104.07   595.4  2106.3
   613.6 2114.14   651.6 2136.07   672.3 2145.84   687.6 2151.12   703.6 2154.41
#Mann= 4 ,-1 , 0
       0      .1       0   179.6    .045       0   197.8      .1       0
  238.57     .12       0
#XS Ineff= 2 , 0
                          211.41         2099.34
Permanent Ineff=
       F       F
Bank Sta=179.6,197.8
XS Rating Curve= 0 ,0
Exp/Cntr(USF)=0,0
Exp/Cntr=0.3,0.1

Type RM Length L Ch R = 1 ,2717    ,232.2,231.8,231.2
XS GIS Cut Line= 4
2462900.67005837553713.9894686612462964.96333371553749.555961402
2463198.88142059553886.3501642552463595.58460886554106.588830848
#Sta/Elev= 30
       0 2179.96    20.7 2171.07    49.3 2152.93    69.9 2137.64    84.8 2123.86
      92 2114.82   103.3 2098.47   107.9 2093.48   113.8 2089.32   125.5 2087.75
   132.72089.187   140.1 2092.68   186.7 2091.53   195.6 2093.72   210.3  2092.7
   228.5 2096.04  307.542096.864     353 2097.11   391.8 2099.25     436 2098.88
     483 2096.83   522.7 2096.91   594.8 2098.06     628 2099.96   641.9 2102.34
   664.6 2109.39     736 2136.83   760.6 2143.38  783.152146.458   798.2 2148.32
#Mann= 5 ,-1 , 0
       0      .1       0   113.8    .045       0   132.7      .1       0
  307.54     .12       0  783.15      .1       0
#XS Ineff= 2 , 0
                          142.93          2094.4
Permanent Ineff=
       F       F
Bank Sta=113.8,132.7
XS Rating Curve= 0 ,0
Exp/Cntr(USF)=0,0
Exp/Cntr=0.3,0.1

Type RM Length L Ch R = 1 ,2485    ,172.4,172.1,168.5
XS GIS Cut Line= 4
2462752.93231929553902.7654685972462804.91411637553926.020483082
2463153.73933365554121.6361931612463435.53539152554295.364830784
#Sta/Elev= 30
       0 2156.09    10.7 2154.93   28.512144.253    63.6 2126.48    75.1 2119.23
    95.7 2098.97   108.9 2088.75   114.1 2087.23   132.4 2086.22   138.3 2083.57
   150.8 2082.08   169.1 2083.39   178.3 2083.57   187.5 2087.29   216.1 2090.31
   292.9 2090.99   320.4 2092.44   389.2 2089.99     435  2092.5   495.7 2089.93
   535.5 2090.09   575.5 2091.59   622.5 2091.48   655.4 2093.67  668.192095.745
  674.422097.174     693 2101.04   721.2 2104.55   772.9 2107.57   787.9 2109.64
#Mann= 6 ,-1 , 0
       0     .06       0   28.51      .1       0   138.3    .045       0
   169.1      .1       0  668.19     .12       0  674.42      .1       0
#XS Ineff= 2 , 0
                          599.18          2095.2
Permanent Ineff=
       F       F
Bank Sta=138.3,169.1
XS Rating Curve= 0 ,0
Exp/Cntr(USF)=0,0
Exp/Cntr=0.3,0.1

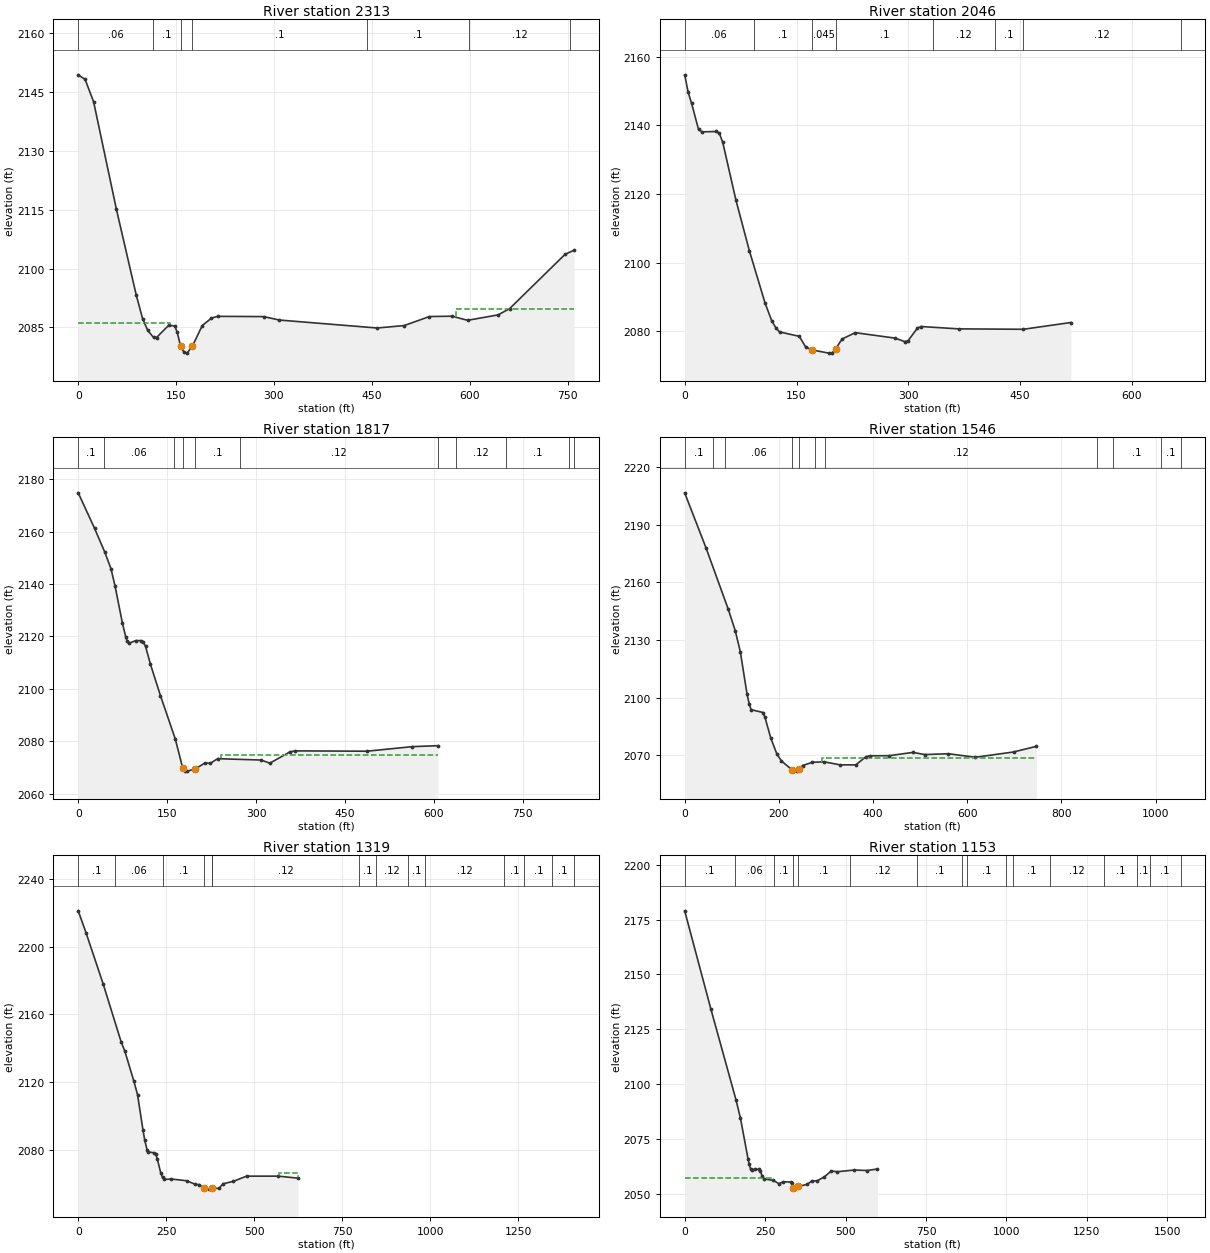
Type RM Length L Ch R = 1 ,2313    ,257.8,267.5,264.2
XS GIS Cut Line= 4
2462705.05434829554062.8146859352462809.01794246554107.956772876
2462895.19829026 554159.938569962463368.50623213554432.159033637
#Sta/Elev= 30
       0 2149.45    10.6 2148.27    23.6 2142.57    58.5 2115.17    89.1 2093.16
    98.6 2087.29   106.5 2084.24   115.4 2082.47     120 2082.44   138.7 2085.57
   148.1 2085.38   151.7 2083.77   156.92080.225   162.1 2078.64   166.7 2078.46
     175 2080.24   190.1 2085.49   204.1 2087.38   213.5 2087.84   284.1 2087.78
   308.2  2086.9     458 2084.87   499.6 2085.49   538.1 2087.79   572.9 2087.88
   596.7 2086.83   643.5 2088.22   661.1 2089.81   746.1 2103.67     760 2104.71
#Mann= 7 ,-1 , 0
       0     .06       0  115.05      .1       0   156.9    .045       0
     175      .1       0  442.62      .1       0   598.5     .12       0
  754.37      .1       0
#XS Ineff= 2 , 0
          139.95 2086.13  579.42         2089.78
Permanent Ineff=
       F       F
Bank Sta=156.9,175
XS Rating Curve= 0 ,0
Exp/Cntr(USF)=0,0
Exp/Cntr=0.3,0.1

Type RM Length L Ch R = 1 ,2046    ,231,228.2,224.5
XS GIS Cut Line= 3
2462666.75197149554296.7327728132462726.94142075554332.299265554
2463132.46023543554522.899188195
#Sta/Elev= 30
       0 2154.78     4.6 2149.76     9.3 2146.44    18.6 2138.83    23.2 2138.14
    42.5 2138.25    46.5 2137.72    51.1 2135.04    68.7 2118.26    86.7 2103.51
   107.8  2088.2   116.8    2083   122.7 2080.82   127.2 2079.77   153.7 2078.48
   162.5 2075.31   171.4 2074.49   193.4 2073.58   197.9  2073.7   202.3 2074.74
   211.1  2077.7   228.8 2079.55   282.2 2077.96   295.1 2076.95   299.5 2077.15
   312.2 2080.89   317.2 2081.34   367.5 2080.66   454.2 2080.54     518 2082.51
#Mann= 8 ,-1 , 0
       0     .06       0   92.83      .1       0   171.4    .045       0
   202.3      .1       0  333.52     .12       0  416.13      .1       0
  453.87     .12       0  665.22      .1       0
#XS Ineff= 2 , 0
                           226.3         2079.14
Permanent Ineff=
       F       F
Bank Sta=171.4,202.3
XS Rating Curve= 0 ,0
Exp/Cntr(USF)=0,0
Exp/Cntr=0.3,0.1

Type RM Length L Ch R = 1 ,1817    ,269,271.5,269.3
XS GIS Cut Line= 3
2462536.64548522554478.8210561652462608.08245783 554525.93905937
2463105.10139486554682.492424857
#Sta/Elev= 30
       0 2174.78    27.6 2161.23    44.9 2152.11    55.2  2145.9    62.2 2139.19
    74.4 2125.26      80 2119.96    82.4 2118.24    85.3 2117.38    96.8 2118.42
   105.1 2118.45   109.3 2118.05   113.5 2116.28   121.9 2109.36   138.7 2097.45
   163.9  2080.8   176.4  2069.7   180.6 2068.73   184.1 2068.66   197.4 2069.48
   214.2 2071.83   222.6  2071.6   235.2 2073.41   308.6 2072.89   323.2  2071.7
   356.8 2075.95   365.2 2076.38   487.1 2076.26   563.6    2078   606.7 2078.36
#Mann= 11 ,-1 , 0
       0      .1       0   42.91     .06       0   161.6      .1       0
   176.4    .045       0   197.4      .1       0  272.76     .12       0
  606.26      .1       0  636.78     .12       0  721.38      .1       0
  827.38     .12       0  836.52      .1       0
#XS Ineff= 2 , 0
                          240.69         2074.81
Permanent Ineff=
       F       F
Bank Sta=176.4,197.4
XS Rating Curve= 0 ,0
Exp/Cntr(USF)=0,0
Exp/Cntr=0.3,0.1

Type RM Length L Ch R = 1 ,1546    ,218.2,227.2,234.2
XS GIS Cut Line= 3
2462348.82189486554623.4609621932462456.90620328554704.524193513
2463041.23699572554886.916463983
#Sta/Elev= 30
       0 2206.53    45.7 2177.66    92.5 2146.07   107.4 2134.87   118.1 2124.02
   132.4 2101.99     137 2096.81   141.2 2093.81   166.4 2092.34   170.6 2089.78
     183 2078.94   195.9 2070.72   205.5 2067.17   227.62062.626   237.5 2061.87
   243.12062.794   250.4 2064.77   271.1 2066.46   296.3 2066.71   329.8 2065.14
   363.3 2065.12   384.4 2069.23   392.6 2069.84   434.5  2069.9   484.8 2071.61
     510 2070.48   560.3  2070.9   617.5 2069.07   698.5 2071.83   747.2 2074.76
#Mann= 11 ,-1 , 0
       0      .1       0   59.82      .1       0   85.87     .06       0
   227.6    .045       0   243.1     .06       0  276.38      .1       0
  298.77     .12       0  876.27      .1       0  909.54      .1       0
 1010.61      .1       0 1053.32      .1       0
#XS Ineff= 2 , 0
                          291.81         2068.56
Permanent Ineff=
       F       F
Bank Sta=227.6,243.1
XS Rating Curve= 0 ,0
Exp/Cntr(USF)=0,0
Exp/Cntr=0.3,0.1

Type RM Length L Ch R = 1 ,1319    ,173.7,170.9,168.2
XS GIS Cut Line= 3
2462243.51624938554722.8040974152462414.48294095554860.411434533
2462743.38903463555095.524288374
#Sta/Elev= 30
       0 2221.05    22.3 2208.06    70.9 2177.91   121.8 2143.86   132.5 2138.26
   158.2 2120.48   168.5 2112.62   183.9 2091.92     189 2085.76   195.8  2079.9
   199.3 2078.82   214.7 2078.41   219.8 2077.56   224.3 2074.97   234.5 2066.45
   239.5 2063.87   244.4 2062.62     264 2062.92   308.3 2061.87   332.9 2059.71
   342.7 2059.61   357.5 2057.54   370.5 2056.93   379.1 2057.56   399.2 2057.31
   411.5 2060.07     441 2061.55   478.2 2064.59   568.4 2064.59   623.8  2063.4
#Mann= 14 ,-1 , 0
       0      .1       0  104.14     .06       0  240.04      .1       0
   357.5    .045       0   379.1      .1       0  379.94     .12       0
  798.67      .1       0  845.48     .12       0  935.79      .1       0
  985.95     .12       0 1209.99      .1       0 1267.29      .1       0
 1346.32      .1       0 1408.66      .1       0
#XS Ineff= 2 , 0
                          569.51         2066.61
Permanent Ineff=
       F       F
Bank Sta=357.5,379.1
XS Rating Curve= 0 ,0
Exp/Cntr(USF)=0,0
Exp/Cntr=0.3,0.1

Type RM Length L Ch R = 1 ,1153    ,279.8,288.2,292.5
XS GIS Cut Line= 3
2462112.38747017554908.8710891322462271.13629818555000.067224367
2462648.04928154555176.418624326
#Sta/Elev= 30
       0    2179    81.1 2134.41   159.6 2092.83   173.4  2084.5   196.9 2066.03
   200.3 2063.66   204.7 2061.49   208.6 2060.81     218 2061.38   231.2  2061.2
   235.6 2060.49   240.1 2058.34   246.4 2056.88   275.2  2056.2   293.1 2054.69
   306.3 2055.59   329.3 2055.45   332.8  2055.1   337.2 2052.65   344.4 2052.22
   353.7 2053.43   381.4 2054.43   394.6 2055.88   412.3 2056.06   434.4 2057.83
   455.7  2060.5   474.1 2060.14   527.1 2060.93   567.3  2060.7   599.2 2061.38
#Mann= 16 ,-1 , 0
       0      .1       0  157.08     .06       0   276.9      .1       0
   337.2    .045       0   353.7      .1       0   512.4     .12       0
   721.9      .1       0  862.41     .12       0  878.49      .1       0
  998.19     .12       0 1020.26      .1       0 1133.98     .12       0
  1303.8      .1       0 1405.54      .1       0 1445.57      .1       0
 1541.32      .1       0
#XS Ineff= 2 , 0
          273.14 2057.23  609.05         2061.96
Permanent Ineff=
       F       F
Bank Sta=337.2,353.7
XS Rating Curve= 0 ,0
Exp/Cntr(USF)=0,0
Exp/Cntr=0.3,0.1

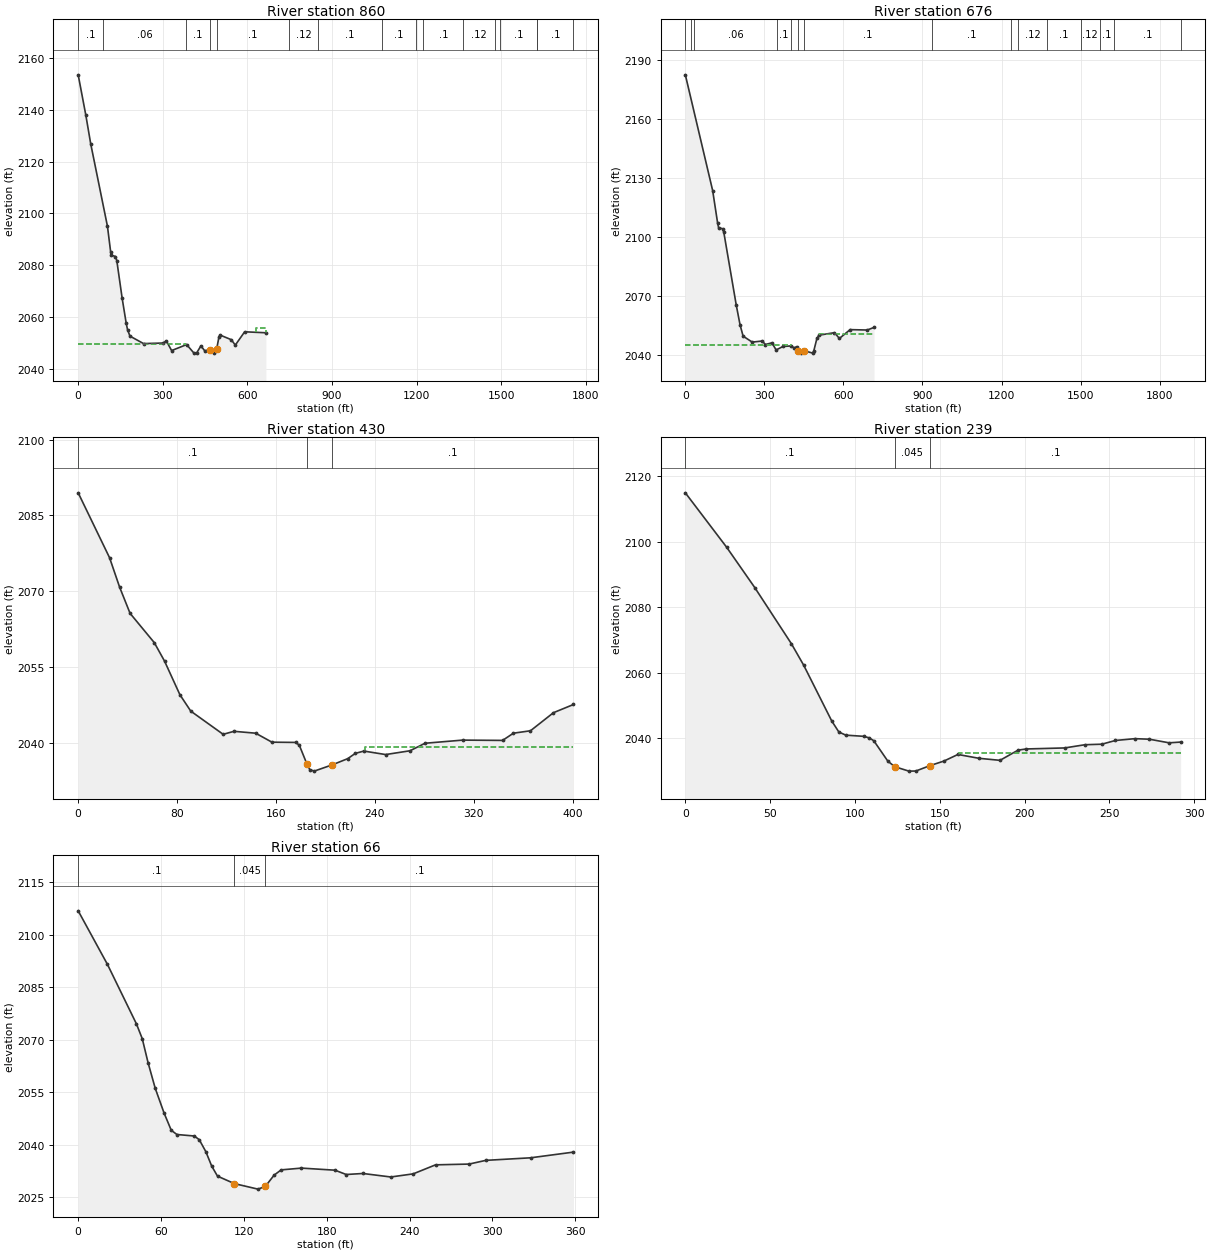
Type RM Length L Ch R = 1 ,860     ,181.2,183.5,146.1
XS GIS Cut Line= 4
2461967.14918073555081.1304556872462277.89156745 555278.72208203
2462429.88512618555396.9392943712462532.48594447555419.101632181
#Sta/Elev= 30
       0 2153.54    27.1 2137.96    44.4 2126.88   103.8 2094.98   115.1 2085.12
     118 2083.84   132.2 2083.29     137 2081.65   155.9 2067.18   170.2 2057.54
   174.9 2055.07   183.5 2052.53   231.8 2049.64   301.5 2049.85   312.4 2050.69
   331.3 2046.94   384.5 2049.25   409.9 2046.04     420 2046.03   435.2 2048.76
   448.8 2046.83   466.2 2047.24   480.8 2045.95   490.9 2047.44   498.8 2052.02
   502.9 2052.94   542.8 2051.15   557.1 2049.05   590.3  2054.2   665.8 2053.82
#Mann= 16 ,-1 , 0
       0      .1       0   87.74     .06       0  381.99      .1       0
   466.2    .045       0   490.9      .1       0  748.45     .12       0
  849.41      .1       0 1076.26      .1       0 1197.44     .12       0
 1223.44      .1       0 1366.03     .12       0 1478.03      .1       0
 1496.09      .1       0 1626.15      .1       0 1627.01      .1       0
 1756.21      .1       0
#XS Ineff= 2 , 0
          383.34 2049.49     631          2055.5
Permanent Ineff=
       F       F
Bank Sta=466.2,490.9
XS Rating Curve= 0 ,0
Exp/Cntr(USF)=0,0
Exp/Cntr=0.3,0.1

Type RM Length L Ch R = 1 ,676     ,209.2,245.6,245.7
XS GIS Cut Line= 3
2461862.44250694555241.5681010082462112.38747017555395.250477052
2462527.83653069555472.936073734
#Sta/Elev= 30
       0 2182.25   103.7  2123.4   122.4 2106.97   126.2 2104.54   141.2 2103.98
   145.9 2102.26   193.1 2065.27   207.6 2055.16   219.3 2049.36   253.9 2046.34
   291.5  2046.9   303.9 2045.12   328.4 2045.97   344.6 2042.36   370.5 2044.12
   401.6  2044.4   413.8 2043.33     422 2044.03   428.8 2041.83   438.2 2040.74
   450.4 2041.97     483 2040.77   487.1 2041.67   499.3  2048.2   507.4 2049.87
     566 2051.14   584.7  2048.2   625.4 2052.69   690.5 2052.49   716.1 2053.82
#Mann= 15 ,-1 , 0
       0     .06       0   19.97      .1       0   32.54     .06       0
  346.89      .1       0  400.19      .1       0   428.8    .045       0
   450.4      .1       0  935.49      .1       0 1236.11      .1       0
 1264.25     .12       0 1374.36      .1       0 1501.32     .12       0
 1572.03      .1       0 1628.28      .1       0 1879.82      .1       0
#XS Ineff= 2 , 0
          399.31 2044.76  507.85         2050.48
Permanent Ineff=
       F       F
Bank Sta=428.8,450.4
XS Rating Curve= 0 ,0
Exp/Cntr(USF)=0,0
Exp/Cntr=0.3,0.1

Type RM Length L Ch R = 1 ,430     ,210.3,191.5,176.4
XS GIS Cut Line= 4
2461959.57908748555525.8003537822462186.81494053555627.135261222
2462232.87626209555627.1352612222462324.99890522555574.932430117
#Sta/Elev= 30
       0 2089.46    25.4 2076.61    33.5 2070.81      42  2065.6    61.6  2059.8
    69.9 2056.14    82.3  2049.5    91.1 2046.25   117.3 2041.66   126.1 2042.25
   143.6 2041.88   156.8  2040.1   175.9 2040.05   178.9 2039.52   185.12035.776
   187.4 2034.67     191 2034.37   205.72035.625   218.1 2036.84   224.3 2037.89
   231.2 2038.34   248.8 2037.65   268.5  2038.4   280.7 2039.89   311.1 2040.51
   343.4 2040.45   352.2 2041.88     366 2042.36   384.6 2045.94   400.8 2047.56
#Mann= 3 ,-1 , 0
       0      .1       0   185.1    .045       0   205.7      .1       0
#XS Ineff= 2 , 0
                          231.77          2039.2
Permanent Ineff=
       F       F
Bank Sta=185.1,205.7
XS Rating Curve= 0 ,0
Exp/Cntr(USF)=0,0
Exp/Cntr=0.3,0.1

Type RM Length L Ch R = 1 ,239     ,173.4,172.5,148.8
XS GIS Cut Line= 3
  2462003.148079 555823.376276452462187.01425973555775.988085541
2462246.69465856555693.156488796
#Sta/Elev= 30
       0 2114.87    24.4 2098.24    40.9    2086    62.5 2068.88    69.8 2062.28
    86.3 2045.31    90.5 2041.94    94.6 2040.98   105.2 2040.62   108.4 2040.15
   111.1 2039.28   119.4 2033.04   123.5 2031.35   131.8 2030.01   135.9 2030.04
   144.2 2031.69   152.4 2033.07   160.7 2035.09   173.1 2033.92   185.5  2033.3
   196.2 2036.42   201.1 2036.77   223.6 2037.08   235.6 2038.06   245.5 2038.22
   253.5 2039.35     265 2039.91   273.6 2039.74   285.2 2038.64     292 2038.87
#Mann= 3 ,-1 , 0
       0      .1       0   123.5    .045       0   144.2      .1       0
#XS Ineff= 2 , 0
                           161.3         2035.41
Permanent Ineff=
       F       F
Bank Sta=123.5,144.2
XS Rating Curve= 0 ,0
Exp/Cntr(USF)=0,0
Exp/Cntr=0.3,0.1

Type RM Length L Ch R = 1 ,66      ,,,
XS GIS Cut Line= 3
2462067.99030879555988.5208643852462209.53389479555943.960846569
2462240.98802502555736.014096758
#Sta/Elev= 30
       0 2106.79    21.2 2091.48    42.2 2074.47    46.4 2070.26    50.6 2063.41
    55.8 2056.07    62.2 2049.01    67.4 2044.08    71.5 2042.87    84.1 2042.44
    87.7 2041.38    92.5 2037.93    96.7 2033.84   100.9 2030.97   113.2 2028.83
   130.2 2027.26   135.5 2028.02   141.9 2031.26     147 2032.76   161.7 2033.27
     186 2032.67   194.1 2031.44   206.2 2031.73   226.4 2030.73   242.6 2031.62
   258.8  2034.2   283.1 2034.42   295.2 2035.48   327.6 2036.21358.7042 2037.84
#Mann= 3 , 0 , 0
       0      .1       0   113.2    .045       0   135.5      .1       0
Bank Sta=113.2,135.5
XS Rating Curve= 0 ,0
Exp/Cntr(USF)=0,0
Exp/Cntr=0.3,0.1
LCMann Table=0

Chan Stop Cuts=-1
Use User Specified Reach Order=0
Composite Channel Slope=5